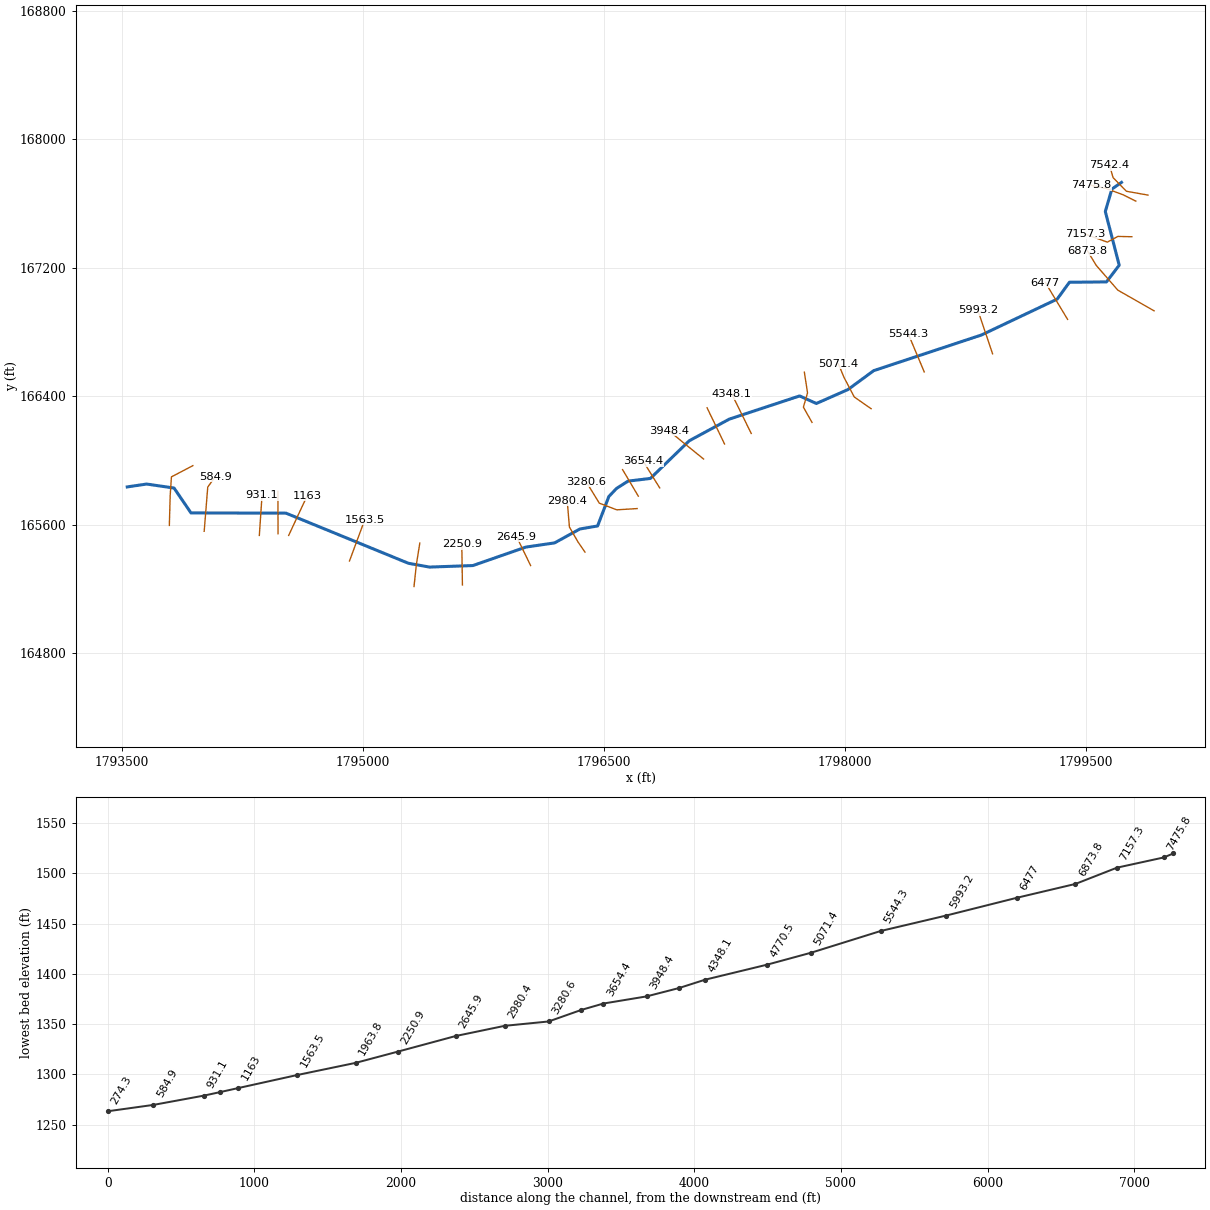
--- Upper Shannon Branch.prj (project) ---

Proj Title=Upper Shannon Branch
Current Plan=p01
Default Exp/Contr=0,0
English Units
Geom File=g01
Flow File=f01
Plan File=p01
BEGIN DESCRIPTION:
END DESCRIPTION:
DSS Export Rating Curves= 0
DSS Export Rating Curve Sorted= 0
DSS Export Volume Flow Curves= 0
DXF OffsetX= 0
DXF OffsetY= 0
DXF ScaleX= 0
DXF ScaleY= 0

--- Upper Shannon Branch.p01 (plan) ---

Plan Title=Floodplain
Program Version=4.00
Geom File=g01
Flow File=f01
K Sum by GR=0
Std Step Tol=0.01
Critical Tol=0.01
Num of Std Step Trials=20
Max Error Tol=0.3
Flow Tol Ratio=0.001
Split Flow NTrial=30
Split Flow Tol=0.02
Split Flow Ratio=0.02
Log Output Level=0
Friction Slope Method=1
Unsteady Friction Slope Method=2
Unsteady Bridges Friction Slope Method=1
Global Log Level=0
CheckData=False
Run HTab=0
Run UNet=0
Run PostProcess=0
UNET Theta=0
UNET Theta Warmup=0
UNET ZTol=0
UNET ZSATol=0
UNET MxIter=0
UNET MaxInSteps=0
UNET DtIC=0
UNET DtMin=0
UNET MaxCRTS=0
UNET WFStab=0
UNET SFStab=0
UNET WFX=0
UNET SFX=0
UNET DSS MLevel=0
UNET DZMax Abort=0
UNET Convert EG Bridges=0
UNET Use Existing IB Tables=0
UNET Froude Limit=0
UNET Froude Power=0
Write IC File=0
Echo Input=False
Echo Output=False
Write Detailed=0

--- Upper Shannon Branch.f01 (steady flow) ---

Flow Title=NFF Regression Equation
Program Version=4.00
Number of Profiles=1
Profile Names=P100yr
River Rch & RM=Upper Shannon...,Main      ,7542.4
521.7664
River Rch & RM=Upper Shannon...,Main      ,7157.3
577.2828
River Rch & RM=Upper Shannon...,Main      ,6873.8
672.5089
River Rch & RM=Upper Shannon...,Main      ,5544.3
693.2940
River Rch & RM=Upper Shannon...,Main      ,4770.5
770.3189
River Rch & RM=Upper Shannon...,Main      ,3654.4
851.0740
River Rch & RM=Upper Shannon...,Main      ,2980.4
945.2100
River Rch & RM=Upper Shannon...,Main      ,274.3
1002.798
Boundary for River Rch & Prof#=Upper Shannon...,Main      ,1
Up Type=0
Dn Type=3
Dn Slope=0.028309

--- Upper Shannon Branch.g01 (geometry) ---

Geom Title=Geometry
Program Version=4.00

River Reach=Upper Shannon...,Main
Reach XY= 30
     1799723.849      167730.817     1799663.813      167689.133
     1799623.043       167549.26     1799709.601      167214.945
     1799630.266      167110.948     1799399.563      167108.806
     1799323.168      167003.762     1798851.547      166780.273
     1798180.408      166558.233     1798021.091      166440.941
     1797823.513      166353.755     1797719.392      166400.798
     1797281.584      166256.534     1797031.945      166121.679
     1796789.833      165887.094     1796650.697       165870.26
     1796578.791      165824.562      1796531.07      165774.228
     1796461.163       165591.04      1796350.77      165572.223
     1796193.335      165485.665     1796014.289      165459.482
     1795684.649      165344.538     1795414.399      165335.058
     1795283.289      165358.597     1794520.484      165670.934
     1793929.001      165672.236      1793823.61       165827.14
     1793653.575      165852.128     1793532.081       165834.26

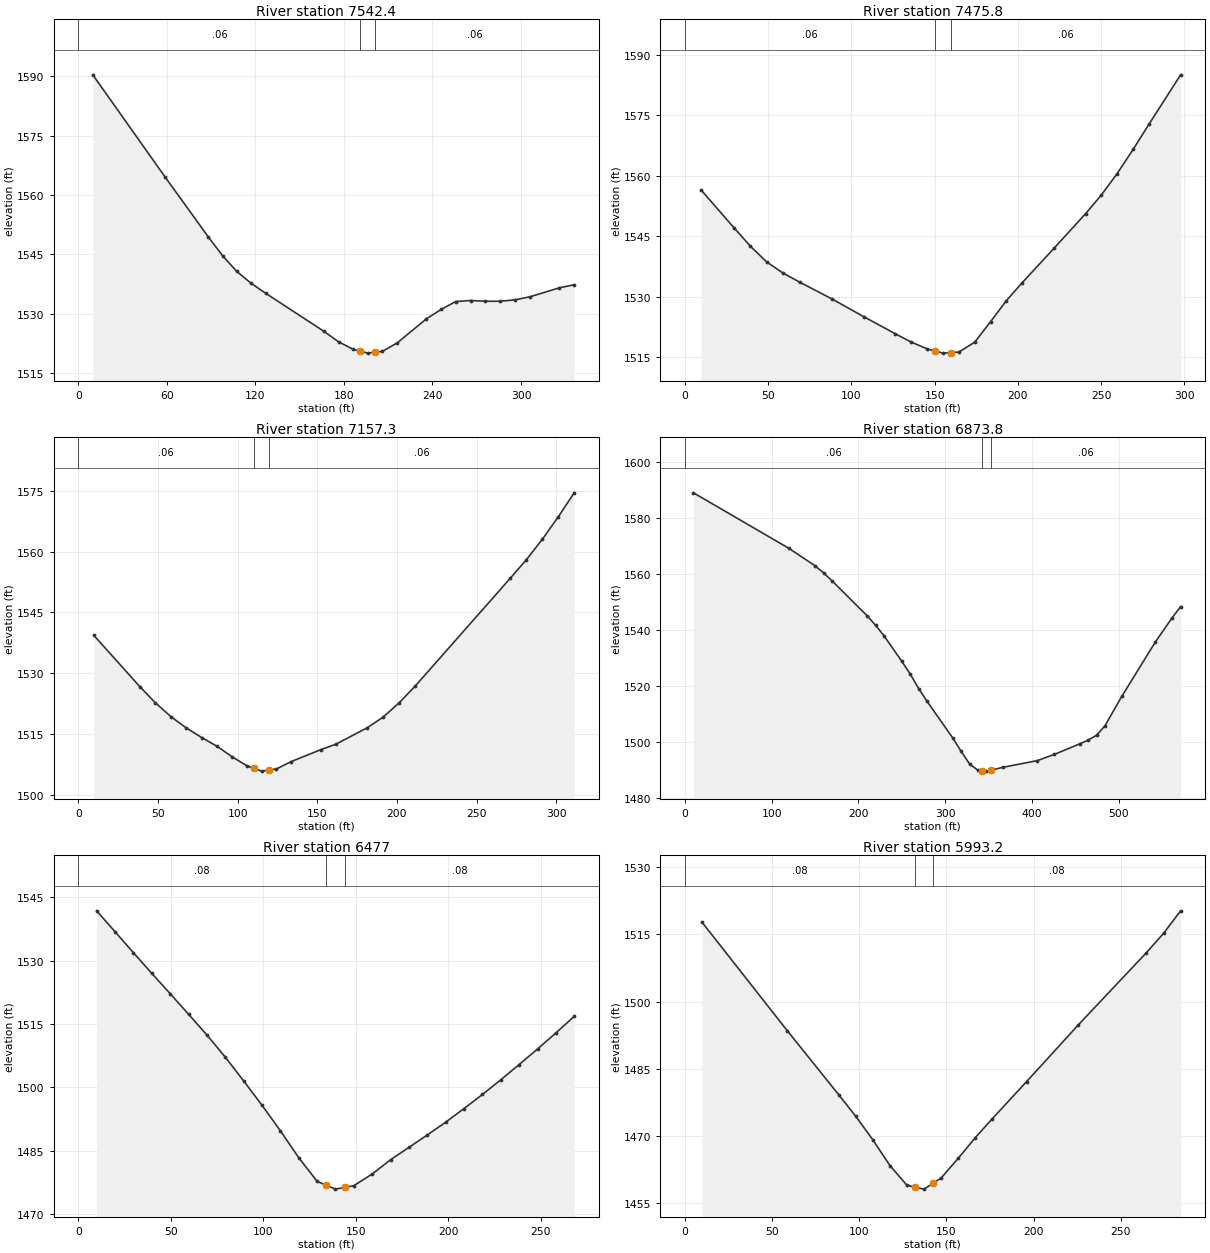
Type RM Length L Ch R = 1 ,7542.4  ,58.2,66.6,75
XS GIS Cut Line= 4
     1799889.078      167651.626     1799754.444      167675.385
     1799671.288      167760.521     1799649.509      167837.738
#Sta/Elev= 25
     9.8 1590.38    58.6 1564.64    87.9 1549.48    97.7 1544.65   107.4 1540.64
   117.2 1537.63   126.9 1535.14   166.5 1525.49   176.4 1522.84   186.3 1520.94
   191.2 1520.47   196.2 1519.99   201.2 1520.22   206.1 1520.45   216.1 1522.58
   235.9 1528.67   245.8 1531.03   255.7 1533.04   265.8  1533.3   275.8 1533.11
   285.8 1533.11   295.8 1533.46   305.9 1534.23   325.9  1536.5     336 1537.29
#Mann= 3 , 0 , 0
       0     .06       0   191.2    .045       0   201.2     .06       0
Bank Sta=191.2,201.2
XS Rating Curve= 0 ,0
Exp/Cntr=0.3,0.1

Type RM Length L Ch R = 1 ,7475.8  ,301.3,318.4,335.6
XS GIS Cut Line= 4
     1799813.049       167613.91     1799733.853      167653.508
     1799626.938      167693.106     1799533.882      167712.905
#Sta/Elev= 26
     9.8 1556.48    29.5 1547.11    39.4  1542.5    49.2 1538.59      59 1535.83
    68.9  1533.6    88.5 1529.37   107.5 1524.99   126.5 1520.72     136 1518.68
   145.6 1516.98   150.1 1516.49   155.1 1515.94   160.1 1516.08   164.6  1516.2
   174.1 1518.68   183.6 1523.76   193.1    1529   202.6 1533.45   221.6 1541.96
   240.6 1550.58   250.1 1555.23   259.6 1560.57   269.2 1566.57   278.7 1572.83
   297.7  1585.1
#Mann= 3 , 0 , 0
       0     .06       0   150.1    .045       0   160.1     .06       0
Bank Sta=150.1,160.1
XS Rating Curve= 0 ,0
Exp/Cntr=0.3,0.1

Type RM Length L Ch R = 1 ,7157.3  ,311,283.5,256
XS GIS Cut Line= 4
     1799788.102      167392.259     1799700.986      167394.238
     1799635.649        167358.6     1799495.076      167410.078
#Sta/Elev= 25
     9.7 1539.33    38.7 1526.62    48.4 1522.66    58.1 1519.26    67.8 1516.46
    77.5 1514.08    87.1 1511.93    96.4 1509.38   105.7 1507.15     110 1506.52
     115  1505.8     120 1506.08   124.4 1506.34   133.7 1508.17   152.3 1511.11
   161.6 1512.43   181.5 1516.53   191.5 1519.18   201.5 1522.69   211.5  1526.8
   271.3 1553.47   281.3    1558   291.3 1563.02   301.3 1568.57   311.3 1574.51
#Mann= 3 , 0 , 0
       0     .06       0     110    .045       0     120     .06       0
Bank Sta=110,120
XS Rating Curve= 0 ,0
Exp/Cntr=0.3,0.1

Type RM Length L Ch R = 1 ,6873.8  ,400.1,396.8,393.6
XS GIS Cut Line= 4
     1799926.696       166930.94     1799700.986      167059.634
     1799566.352      167214.067     1799510.915      167305.143
#Sta/Elev= 30
      10 1588.98   119.9 1569.17   149.9 1562.97   159.9 1560.38   169.9 1557.48
   209.9 1545.12   219.8  1541.7   229.8 1537.81   249.8 1528.92   259.8 1524.24
   269.6    1519   279.3 1514.47   308.6 1501.49   318.4 1496.66   328.1 1492.16
   337.9 1489.86   342.6 1489.73   347.6 1489.59   352.6 1489.91   367.1 1490.99
   406.2 1493.35   425.7 1495.55   454.9 1499.31   464.7 1500.65   474.4  1502.4
   484.1 1505.78   503.5 1516.29   542.2 1535.72   561.6 1544.39   571.3 1548.33
#Mann= 3 , 0 , 0
       0     .06       0   342.6    .045       0   352.6     .06       0
Bank Sta=342.6,352.6
XS Rating Curve= 0 ,0
Exp/Cntr=0.3,0.1

Type RM Length L Ch R = 1 ,6477    ,488.2,483.8,479.4
XS GIS Cut Line= 2
     1799388.161      166877.482     1799249.567      167107.152
#Sta/Elev= 29
     9.9 1541.79    19.9 1536.82    29.8 1531.88    39.7    1527    49.7 1522.17
    59.6 1517.32    69.5 1512.42    79.5 1507.15    89.4 1501.54    99.4 1495.73
   109.3 1489.71   119.2 1483.36   129.2 1477.73   134.1 1476.82   139.1  1475.9
   144.1 1476.31     149 1476.71     159 1479.49   168.9 1482.87   178.8 1485.78
   188.8 1488.73   198.7 1491.75   208.6 1494.97   218.6 1498.31   228.5 1501.79
   238.4 1505.38   248.4 1509.08   258.3 1512.88   268.2 1516.78
#Mann= 3 , 0 , 0
       0     .08       0   134.1    .045       0   144.1     .08       0
Bank Sta=134.1,144.1
XS Rating Curve= 0 ,0
Exp/Cntr=0.3,0.1

Type RM Length L Ch R = 1 ,5993.2  ,447.5,448.8,450.2
XS GIS Cut Line= 2
     1798920.902      166663.652     1798829.827       166932.92
#Sta/Elev= 19
     9.8 1517.77    58.8 1493.49    88.2 1479.25      98 1474.42   107.8 1469.17
   117.6 1463.42   127.4    1459   132.2 1458.58   137.2 1458.15   142.2 1459.42
     147 1460.64   156.8 1465.04   166.6 1469.66   176.4 1473.91     196 1482.16
   225.4 1494.71   264.6  1510.9   274.5 1515.24   284.3 1520.27
#Mann= 3 , 0 , 0
       0     .08       0   132.2    .045       0   142.2     .08       0
Bank Sta=132.2,142.2
XS Rating Curve= 0 ,0
Exp/Cntr=0.3,0.1

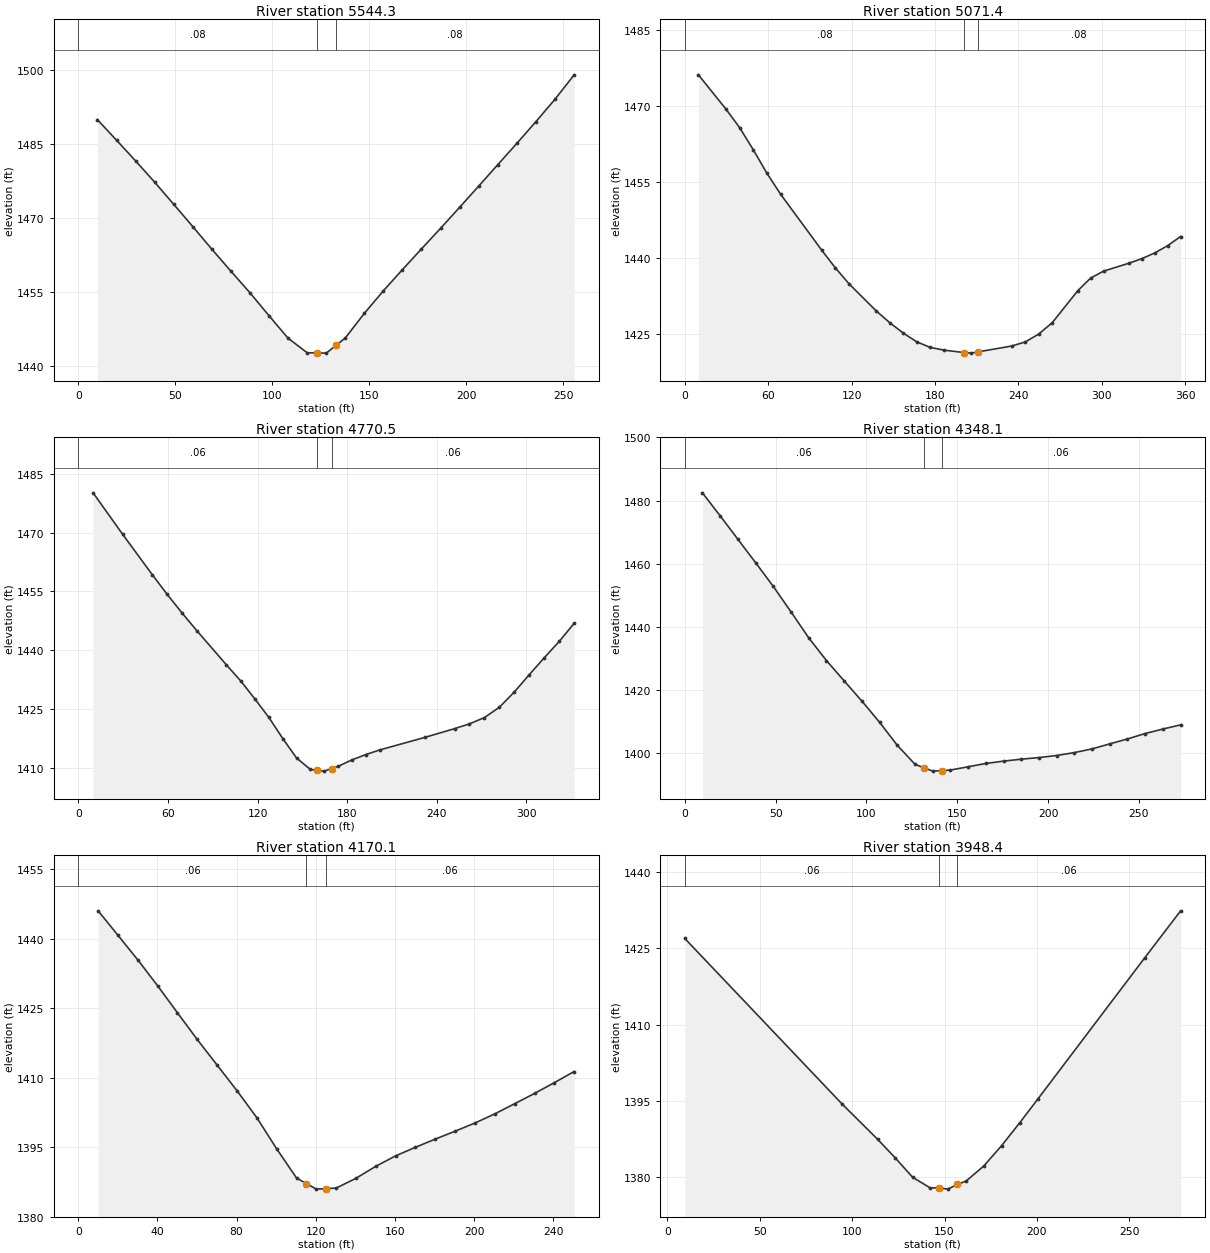
Type RM Length L Ch R = 1 ,5544.3  ,471.3,472.9,474.5
XS GIS Cut Line= 2
     1798495.222      166550.798     1798396.227      166786.407
#Sta/Elev= 28
     9.8    1490    19.7 1485.82    29.5 1481.64    39.3 1477.34    49.1 1472.87
      59 1468.32    68.8 1463.75    78.6 1459.31    88.5  1454.9    98.3 1450.26
   108.1 1445.71     118 1442.75   122.8 1442.72   127.8 1442.68   132.8 1444.24
   137.6 1445.74   147.4 1450.72   157.3 1455.33   167.1 1459.61   176.9  1463.8
   186.8    1468   196.6 1472.24   206.4 1476.53   216.2 1480.85   226.1  1485.2
   235.9 1489.59   245.7 1494.11   255.6 1499.07
#Mann= 3 , 0 , 0
       0     .08       0   122.8    .045       0   132.8     .08       0
Bank Sta=122.8,132.8
XS Rating Curve= 0 ,0
Exp/Cntr=0.3,0.1

Type RM Length L Ch R = 1 ,5071.4  ,316.7,301,285.2
XS GIS Cut Line= 4
     1798164.578      166321.128     1798059.642      166394.385
     1797996.285      166515.159     1797960.647      166600.295
#Sta/Elev= 30
     9.8 1476.21    29.5 1469.46    39.4 1465.78    49.2 1461.41    59.1 1456.72
    68.9 1452.59    98.4 1441.54   108.3 1438.01   118.1 1434.86   137.7 1429.49
   147.5 1427.14   157.2 1425.09   166.9 1423.36   176.7 1422.25   186.4 1421.73
   200.9 1421.24   205.9 1421.13   210.9 1421.38   235.1 1422.53   244.9 1423.34
   254.6  1424.9   264.4 1427.17   282.8 1433.51     292 1435.99   301.3 1437.36
   319.7 1438.94     329 1439.85   338.2 1440.97   347.4 1442.41   356.7 1444.21
#Mann= 3 , 0 , 0
       0     .08       0   200.9    .045       0   210.9     .08       0
Bank Sta=200.9,210.9
XS Rating Curve= 0 ,0
Exp/Cntr=0.3,0.1

Type RM Length L Ch R = 1 ,4770.5  ,406.6,422.4,438.2
XS GIS Cut Line= 4
     1797796.315      166235.992     1797742.857      166331.028
     1797768.596      166420.124     1797748.797      166548.818
#Sta/Elev= 30
     9.9 1480.16    29.7 1469.57    49.6 1459.24    59.5 1454.26    69.4 1449.54
    79.3 1445.03    99.1 1436.32     109 1432.07   118.3 1427.56   127.6 1422.87
   136.9  1417.5   146.1 1412.54   155.4 1409.61   159.7 1409.42   164.7 1409.19
   169.7 1409.85     174 1410.42   183.2 1412.06   192.5 1413.41   201.8 1414.59
   231.8 1417.77   251.9 1420.02   261.9 1421.24   271.9 1422.84   281.9 1425.47
   291.9 1429.36   301.9 1433.77     312 1438.11     322 1442.27     332 1446.89
#Mann= 3 , 0 , 0
       0     .06       0   159.7    .045       0   169.7     .06       0
Bank Sta=159.7,169.7
XS Rating Curve= 0 ,0
Exp/Cntr=0.3,0.1

Type RM Length L Ch R = 1 ,4348.1  ,178.2,178,177.8
XS GIS Cut Line= 3
     1797417.988      166167.241     1797357.615      166289.664
     1797297.242      166412.087
#Sta/Elev= 30
     9.7 1482.46    19.5 1475.14    29.2 1467.77      39 1460.31    48.7 1452.82
    58.5 1444.71    68.3 1436.44      78 1429.29    87.8 1422.81    97.5 1416.45
   107.3 1409.69     117 1402.42   126.8 1396.38   131.5 1395.35   136.5 1394.24
   141.5 1394.41   146.2 1394.57     156 1395.62   165.8 1396.67   175.5 1397.41
   185.3 1398.03     195 1398.54   204.7 1399.19   214.5 1400.12   224.2 1401.28
     234 1402.88   243.7 1404.43   253.5 1406.16   263.2 1407.58     273 1408.91
#Mann= 3 , 0 , 0
       0     .06       0   131.5    .045       0   141.5     .06       0
Bank Sta=131.5,141.5
XS Rating Curve= 0 ,0
Exp/Cntr=0.3,0.1

Type RM Length L Ch R = 1 ,4170.1  ,212.7,221.6,230.4
XS GIS Cut Line= 2
      1797251.84      166101.358     1797142.945      166327.068
#Sta/Elev= 27
      10 1446.06      20 1440.79    30.1 1435.44    40.1 1429.85    50.1 1424.03
    60.1 1418.26    70.2  1412.7    80.2 1407.19    90.2 1401.38   100.2 1394.67
   110.3 1388.32   115.3 1387.12   120.3 1385.93   125.3 1386.04   130.3 1386.15
   140.3 1388.26   150.4 1390.88   160.4 1393.12   170.4 1394.97   180.4 1396.74
   190.5 1398.46   200.5 1400.22   210.5 1402.19   220.5 1404.38   230.6 1406.61
   240.6 1408.94   250.6 1411.34
#Mann= 3 , 0 , 0
       0     .06       0   115.3    .045       0   125.3     .06       0
Bank Sta=115.3,125.3
XS Rating Curve= 0 ,0
Exp/Cntr=0.3,0.1

Type RM Length L Ch R = 1 ,3948.4  ,300.9,294.1,287.4
XS GIS Cut Line= 3
     1797121.253      166008.022     1797010.658      166097.436
     1796905.947       166183.37
#Sta/Elev= 16
     9.5 1426.97    94.8 1394.28   113.8 1387.41   123.3 1383.76   132.7 1379.94
   142.2 1377.84   146.9 1377.84  151.84 1377.59   156.9 1378.52   161.6 1379.16
   171.2 1382.14   180.9 1386.17   190.6 1390.63   200.3 1395.26   258.3 1423.17
   277.7 1432.42
#Mann= 3 , 0 , 0
     9.5     .06       0   146.9    .045       0   156.9     .06       0
Bank Sta=146.9,156.9
XS Rating Curve= 0 ,0
Exp/Cntr=0.3,0.1

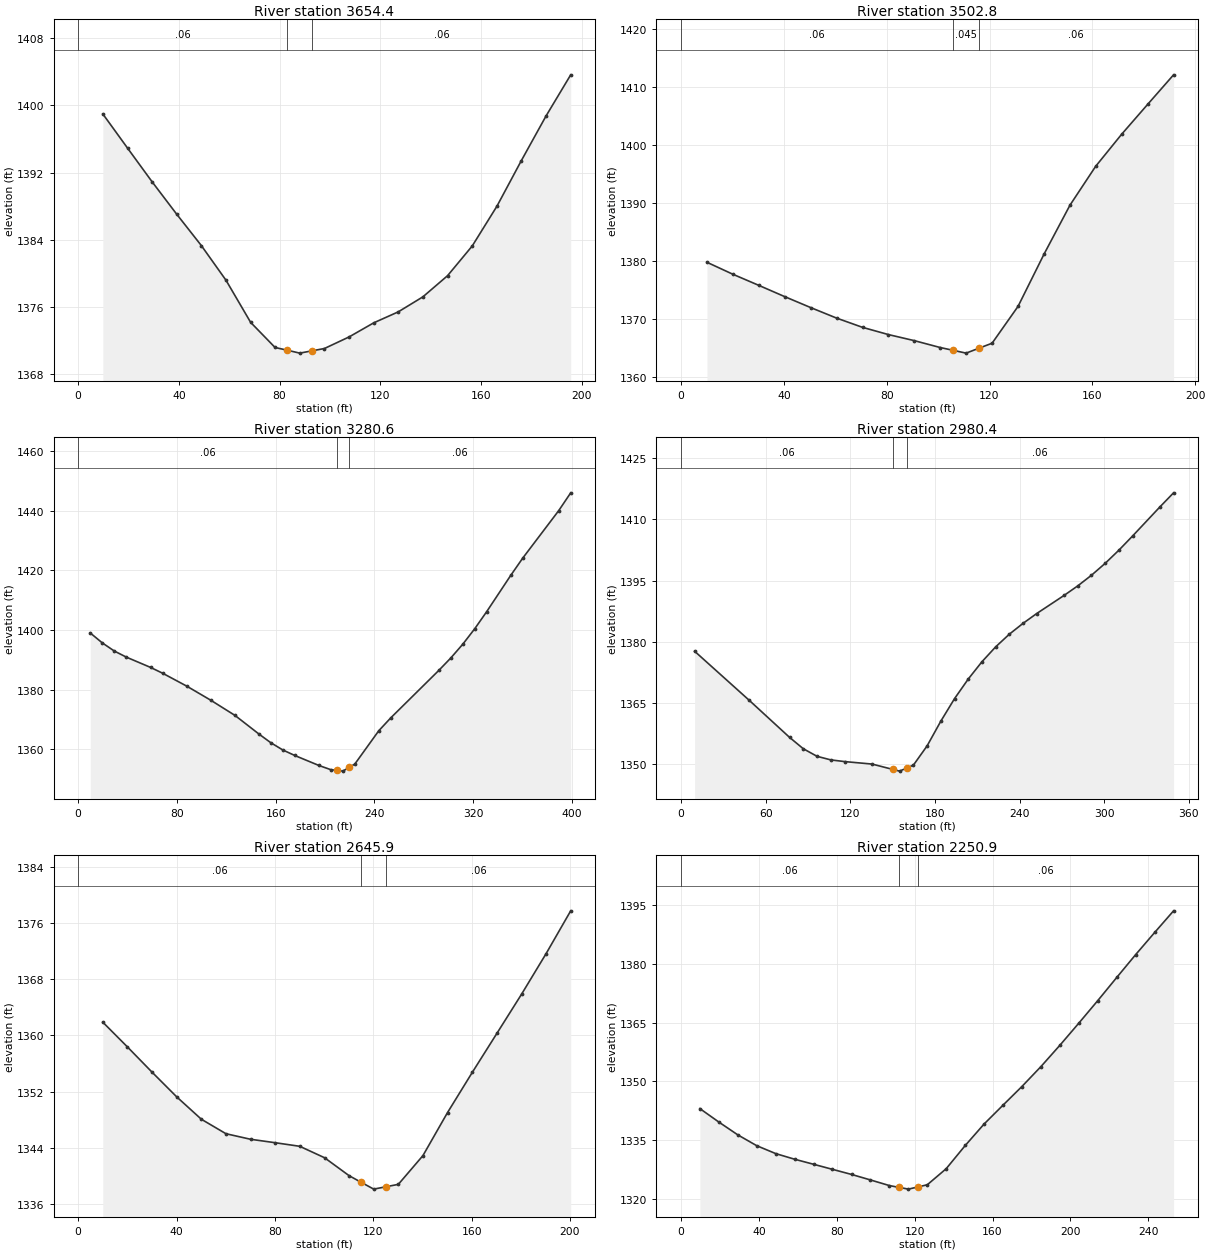
Type RM Length L Ch R = 1 ,3654.4  ,152.2,151.6,151
XS GIS Cut Line= 2
     1796847.939      165828.131     1796744.983      165994.443
#Sta/Elev= 22
     9.8 1398.97    19.6 1394.91    29.3 1390.92    39.1 1387.05    48.9 1383.31
    58.7 1379.18    68.5 1374.16    78.2 1371.17      83 1370.85      88  1370.5
      93 1370.78    97.8 1371.05   107.6 1372.43   117.4 1374.11   127.1 1375.41
   136.9  1377.2   146.7 1379.72   156.5 1383.26   166.3 1387.99     176 1393.42
   185.8 1398.73   195.6 1403.63
#Mann= 3 , 0 , 0
       0     .06       0      83    .045       0      93     .06       0
Bank Sta=83,93
XS Rating Curve= 0 ,0
Exp/Cntr=0.3,0.1

Type RM Length L Ch R = 1 ,3502.8  ,208.9,222.2,235.6
XS GIS Cut Line= 2
     1796714.638      165776.966     1796616.824      165941.706
#Sta/Elev= 21
    10.1 1379.78    20.2 1377.71    30.3 1375.79    40.3 1373.86    50.4 1371.97
    60.5 1370.15    70.6 1368.55    80.7  1367.3    90.8 1366.25   100.8 1365.07
   105.9 1364.58   110.9  1364.1   115.9 1364.95     121 1365.81   131.1 1372.17
   141.2 1381.18   151.3 1389.64   161.3 1396.35   171.4 1401.88   181.5 1407.03
   191.6 1412.14
#Mann= 3 , 0 , 0
       0     .06       0   105.9    .045       0   115.9     .06       0
Bank Sta=105.9,115.9
XS Rating Curve= 0 ,0
Exp/Cntr=0.3,0.1

Type RM Length L Ch R = 1 ,3280.6  ,314.8,300.1,285.5
XS GIS Cut Line= 4
     1796707.365      165699.437     1796580.651      165691.517
     1796471.756      165733.096      1796390.58      165865.749
#Sta/Elev= 30
     9.8 1398.96    19.5 1395.65    29.3  1392.9    39.1 1390.85    58.6 1387.42
    68.4 1385.47    87.9 1381.15   107.4 1376.42     127 1371.33   146.4 1365.09
   156.1 1362.15   165.8 1359.73   175.5 1357.88     195 1354.54   204.7 1353.12
   209.4 1352.89   214.4 1352.64   219.4 1353.86   224.1 1355.01   243.5 1366.17
   253.2 1370.49   292.1 1386.39   301.8 1390.55   311.6 1395.21   321.3 1400.41
     331 1406.15   350.4 1418.26   360.2  1424.1   389.3 1439.99     399 1445.95
#Mann= 3 , 0 , 0
       0     .06       0   209.4    .045       0   219.4     .06       0
Bank Sta=209.4,219.4
XS Rating Curve= 0 ,0
Exp/Cntr=0.3,0.1

Type RM Length L Ch R = 1 ,2980.4  ,335.9,334.5,333.2
XS GIS Cut Line= 4
      1796382.66       165428.19     1796339.102      165491.547
     1796285.645      165584.602     1796271.785      165748.935
#Sta/Elev= 29
     9.6 1377.68    48.1 1365.72    76.9 1356.57    86.6 1353.79    96.4 1351.92
   106.2 1351.04   115.9 1350.63   135.4 1350.02   149.9 1348.73   154.9 1348.29
   159.9 1349.04   164.7 1349.76   174.4 1354.47   184.2 1360.57   193.9 1366.08
   203.6 1370.87   213.3  1375.1     223 1378.74   232.7 1381.85   242.4  1384.5
   252.1 1386.91   271.5 1391.35   281.2 1393.69   290.9 1396.29   300.6  1399.2
   310.3 1402.42     320 1405.89   339.4 1413.03   349.1 1416.49
#Mann= 3 , 0 , 0
       0     .06       0   149.9    .045       0   159.9     .06       0
Bank Sta=149.9,159.9
XS Rating Curve= 0 ,0
Exp/Cntr=0.3,0.1

Type RM Length L Ch R = 1 ,2645.9  ,403.8,395,386.2
XS GIS Cut Line= 2
     1796044.096      165344.524     1795956.578      165524.708
#Sta/Elev= 22
      10  1361.9      20 1358.38      30 1354.79    40.1 1351.25    50.1 1348.07
    60.1 1346.01    70.1 1345.22    80.1 1344.73    90.1 1344.22   100.2 1342.59
   110.2 1340.03   115.2 1339.07   120.2 1338.12   125.2 1338.46   130.2  1338.8
   140.2 1342.89   150.2 1349.02   160.3 1354.76   170.3 1360.31   180.3 1365.87
   190.3 1371.66   200.3 1377.75
#Mann= 3 , 0 , 0
       0     .06       0   115.2    .045       0   125.2     .06       0
Bank Sta=115.2,125.2
XS Rating Curve= 0 ,0
Exp/Cntr=0.3,0.1

Type RM Length L Ch R = 1 ,2250.9  ,289.6,287.1,283.6
XS GIS Cut Line= 2
     1795619.357      165223.499     1795615.465      165476.453
#Sta/Elev= 28
     9.7 1343.07    19.5 1339.62    29.2 1336.37    38.9 1333.62    48.7  1331.6
    58.4 1330.17    68.1 1328.89    77.8  1327.6    87.6  1326.3    97.3  1324.9
     107 1323.47   111.8 1323.02   116.8 1322.56   121.8 1323.13   126.5 1323.67
   136.2 1327.76     146 1333.68   155.7 1339.16   165.4 1343.95   175.1  1348.7
   184.9 1353.79   194.6  1359.2   204.3 1364.82   214.1  1370.6   223.8 1376.47
   233.5 1382.28   243.3 1387.94     253 1393.45
#Mann= 3 , 0 , 0
       0     .06       0   111.8    .045       0   121.8     .06       0
Bank Sta=111.8,121.8
XS Rating Curve= 0 ,0
Exp/Cntr=0.3,0.1

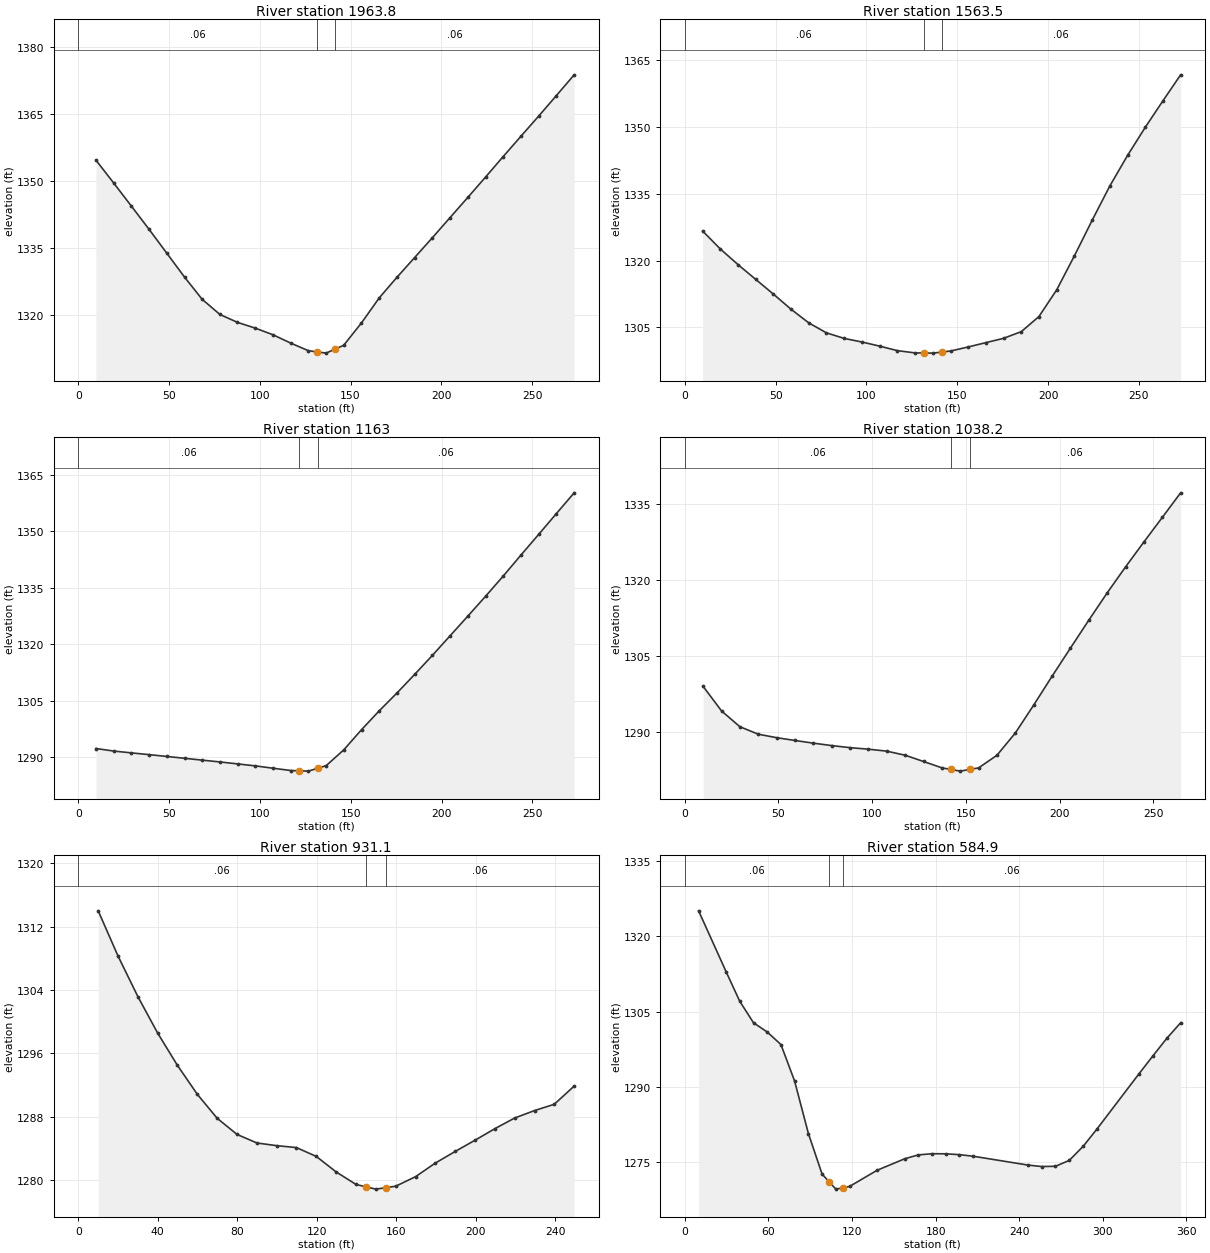
Type RM Length L Ch R = 1 ,1963.8  ,405.3,400.3,396.3
XS GIS Cut Line= 3
       1795317.9      165214.064     1795332.437      165349.748
     1795353.994      165484.759
#Sta/Elev= 30
     9.7 1354.63    19.5  1349.5    29.2 1344.35      39 1339.12    48.7 1333.81
    58.5 1328.44    68.2 1323.47      78 1320.06    87.7 1318.29    97.5    1317
   107.2 1315.52     117 1313.65   126.7 1311.95   131.5 1311.68   136.5  1311.4
   141.5  1312.3   146.2 1313.15     156 1318.16   165.8 1323.78   175.5 1328.36
   185.3 1332.81   195.1 1337.26   204.8 1341.75   214.6 1346.28   224.4 1350.85
   234.1 1355.43   243.9 1359.99   253.7 1364.52   263.4 1369.09   273.2 1373.74
#Mann= 3 , 0 , 0
       0     .06       0   131.5    .045       0   141.5     .06       0
Bank Sta=131.5,141.5
XS Rating Curve= 0 ,0
Exp/Cntr=0.3,0.1

Type RM Length L Ch R = 1 ,1563.5  ,402.1,400.5,398.8
XS GIS Cut Line= 3
     1794916.047      165373.045      1794963.47      165501.042
     1795010.894      165629.039
#Sta/Elev= 30
     9.8 1326.66    19.5 1322.64    29.3 1319.11      39 1315.81    48.8 1312.48
    58.5 1309.09    68.3 1306.02      78 1303.79    87.8 1302.54    97.5 1301.74
   107.3 1300.81     117  1299.8   126.8 1299.29   131.5 1299.27   136.5 1299.24
   141.5 1299.48   146.3 1299.71     156 1300.62   165.8  1301.6   175.5 1302.56
   185.3 1304.07     195 1307.46   204.8 1313.47   214.5 1321.07   224.3 1329.07
     234 1336.75   243.8 1343.63   253.5 1349.91   263.3  1355.9     273 1361.71
#Mann= 3 , 0 , 0
       0     .06       0   131.5    .045       0   141.5     .06       0
Bank Sta=131.5,141.5
XS Rating Curve= 0 ,0
Exp/Cntr=0.3,0.1

Type RM Length L Ch R = 1 ,1163    ,116,124.8,133.7
XS GIS Cut Line= 3
     1794537.425      165532.214     1794594.927      165655.993
     1794652.793       165779.64
#Sta/Elev= 30
     9.7 1292.32    19.5 1291.64    29.2 1291.16      39 1290.69    48.7 1290.21
    58.5 1289.72    68.2 1289.23      78 1288.75    87.7 1288.23    97.5  1287.7
   107.2 1287.08     117 1286.47   121.7  1286.4   126.7 1286.31   131.7 1287.06
   136.5 1287.78   146.2 1291.99     156 1297.36   165.7 1302.35   175.5  1307.1
   185.2 1312.02     195  1317.1   204.7 1322.28   214.5 1327.52   224.2 1332.76
     234 1338.17   243.7 1343.72   253.5 1349.23   263.2 1354.74     273 1360.26
#Mann= 3 , 0 , 0
       0     .06       0   121.7    .045       0   131.7     .06       0
Bank Sta=121.7,131.7
XS Rating Curve= 0 ,0
Exp/Cntr=0.3,0.1

Type RM Length L Ch R = 1 ,1038.2  ,108.7,107,105.4
XS GIS Cut Line= 2
     1794471.335       165542.61     1794470.038      165807.239
#Sta/Elev= 29
     9.8 1298.97    19.6 1294.13    29.4 1291.01    39.2 1289.54      49 1288.85
    58.8  1288.3    68.6 1287.77    78.4 1287.29    88.2 1286.88      98 1286.58
   107.8 1286.19   117.6 1285.39   127.4 1284.15   137.2  1282.9     142 1282.58
     147 1282.25     152 1282.58   156.8 1282.89   166.6 1285.39   176.4 1289.78
   186.2 1295.29     196 1300.98   205.8 1306.53   215.6 1312.04   225.4 1317.42
   235.2 1322.55     245 1327.47   254.8 1332.31   264.6 1337.17
#Mann= 3 , 0 , 0
       0     .06       0     142    .045       0     152     .06       0
Bank Sta=142,152
XS Rating Curve= 0 ,0
Exp/Cntr=0.3,0.1

Type RM Length L Ch R = 1 ,931.1   ,346.4,346.2,346.1
XS GIS Cut Line= 2
     1794354.587      165532.233     1794371.451      165781.295
#Sta/Elev= 27
      10 1314.02      20  1308.3      30 1303.17    39.9 1298.59    49.9 1294.49
    59.9 1290.84    69.9 1287.81    79.9 1285.77    89.9 1284.69    99.9 1284.35
   109.8 1284.11   119.8 1282.99   129.8 1281.03   139.8 1279.45   144.8 1279.15
   149.8 1278.86   154.8 1279.04   159.8 1279.23   169.8 1280.44   179.7 1282.15
   189.7 1283.62   199.7 1285.04   209.7  1286.5   219.7 1287.85   229.7 1288.79
   239.6 1289.58   249.6 1291.88
#Mann= 3 , 0 , 0
       0     .06       0   144.8    .045       0   154.8     .06       0
Bank Sta=144.8,154.8
XS Rating Curve= 0 ,0
Exp/Cntr=0.3,0.1

Type RM Length L Ch R = 1 ,584.9   ,310.3,310.6,310.8
XS GIS Cut Line= 3
     1794011.236      165558.024     1794033.288      165833.031
     1794079.988      165897.891
#Sta/Elev= 30
     9.9 1325.12    29.6 1312.99    39.4 1307.08    49.3 1302.77    59.1 1300.94
      69 1298.42    78.8 1291.13    88.7 1280.65    98.5 1272.57   103.4 1271.08
   108.4 1269.56   113.4 1269.83   118.2 1270.09   137.9 1273.31   157.7 1275.61
   167.5 1276.39   177.4 1276.63   187.2 1276.61   197.1 1276.44   206.9 1276.13
   246.3 1274.36   256.2 1274.07     266 1274.12   275.9  1275.3   285.9 1278.12
   295.9 1281.61   325.8 1292.54   335.8 1296.12   345.8 1299.64   355.8 1302.77
#Mann= 3 , 0 , 0
       0     .06       0   103.4    .045       0   113.4     .06       0
Bank Sta=103.4,113.4
XS Rating Curve= 0 ,0
Exp/Cntr=0.3,0.1

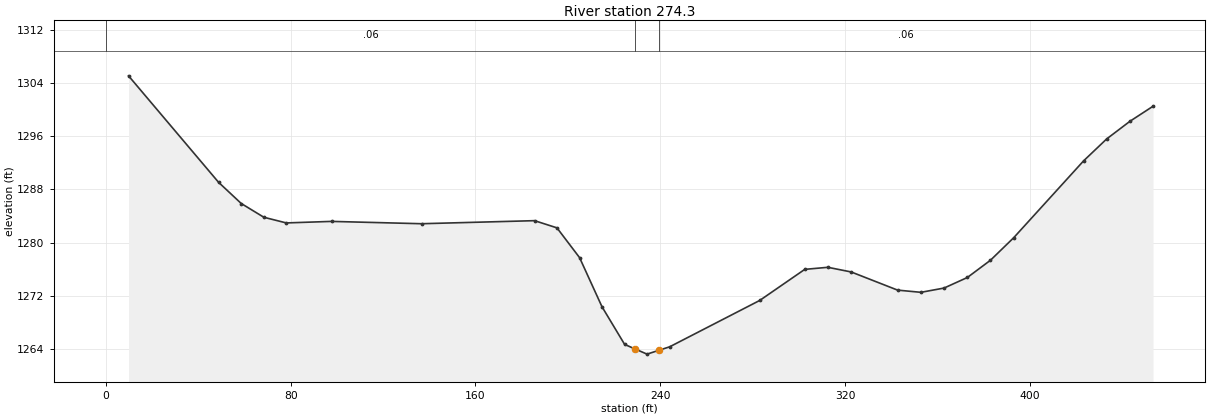
Type RM Length L Ch R = 1 ,274.3   ,269.4,274.3,279.2
XS GIS Cut Line= 4
     1793794.197      165594.498     1793799.386      165779.998
     1793807.169      165896.746      1793940.78      165966.795
#Sta/Elev= 30
     9.8 1305.08    48.8 1289.07    58.6 1285.89    68.4 1283.82    78.1 1282.97
    97.7  1283.2   136.7 1282.85   185.6 1283.31   195.3 1282.23   205.1 1277.75
   214.8 1270.37   224.6 1264.71   229.3    1264   234.3 1263.25   239.3 1263.81
   244.1 1264.35   283.1 1271.32   302.6 1275.99   312.6  1276.3   322.7  1275.6
   342.8 1272.87   352.9 1272.54   362.9 1273.18     373 1274.77     383 1277.36
   393.1 1280.76   423.3 1292.29   433.3 1295.59   443.4 1298.25   453.4 1300.51
#Mann= 3 , 0 , 0
       0     .06       0   229.3    .045       0   239.3     .06       0
Bank Sta=229.3,239.3
XS Rating Curve= 0 ,0
Exp/Cntr=0.3,0.1
Stream Node=Upper Shannon...,Main            , 0 , 0 ,Upstream end
Stream Node=Upper Shannon...,Main            , 0 , 1 ,Downstream end

Chan Stop Cuts=-1
Use User Specified Reach Order=0